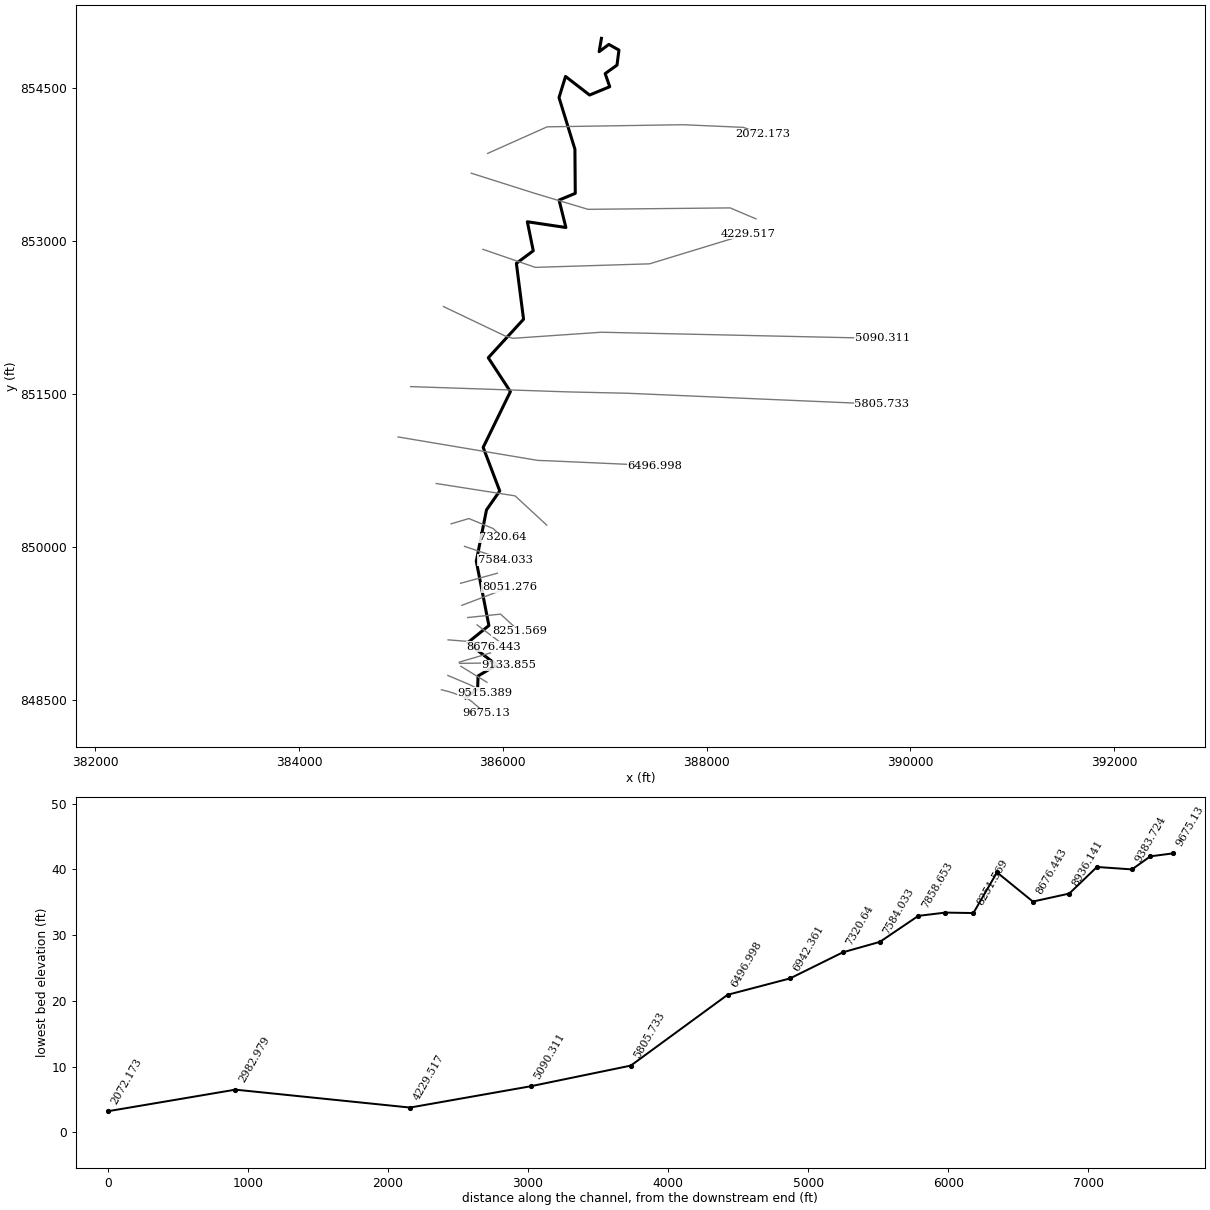
--- 6945_ras.prj (project) ---

Proj Title=6945
Current Plan=p01
Default Exp/Contr=0.3,0.1
English Units
Geom File=g01
Flow File=f01
Plan File=p01
Y Axis Title=Elevation
X Axis Title(PF)=Main Channel Distance
X Axis Title(XS)=Station
BEGIN DESCRIPTION:
RFD model 6945 exported to HEC-RAS
END DESCRIPTION:

--- 6945_ras.p01 (plan) ---

Plan Title=Plan 01
Program Version=4.10
Short Identifier=Plan 01
Geom File=g01
Flow File=f01
Subcritical Flow
Calc Critical at every XS
Secant Critical Depth

--- 6945_ras.f01 (steady flow) ---

Flow Title=Flow 01
Program Version=5.01
Number of Profiles= 6
Profile Names=10yr,25yr,50yr,100yr,100plus,500yr
River Rch & RM=6945,19, 9675.13
  365.95  615.43  858.86 1093.81 1596.96 2613.58
River Rch & RM=6945,19,9515.389
  370.77  623.66  870.46  1108.7 1618.71  2644.7
River Rch & RM=6945,19,9383.724
  376.26  633.09  883.81 1125.89  1643.8 2680.82
River Rch & RM=6945,19,9133.855
  378.92  637.63  890.22 1134.12 1655.81 2697.95
River Rch & RM=6945,19,8936.141
  384.47  647.12  903.62 1151.33 1680.94 2733.79
River Rch & RM=6945,19,8676.443
  386.07  649.84  907.45 1156.24 1688.12    2744
River Rch & RM=6945,19,8420.209
  387.39   652.1  910.64 1160.34  1694.1  2752.5
River Rch & RM=6945,19,8251.569
  389.51  655.72  915.74 1166.89 1703.65 2766.07
River Rch & RM=6945,19,8051.276
  393.99  663.37  926.53 1180.75  1723.9 2794.81
River Rch & RM=6945,19,7858.653
  399.15  672.23  939.08 1196.92  1747.5 2828.49
River Rch & RM=6945,19,7584.033
  401.71  676.64  945.32 1204.96 1759.24 2845.27
River Rch & RM=6945,19, 7320.64
  403.76  680.15  950.31 1211.39 1768.62 2858.66
River Rch & RM=6945,19,6942.361
  417.25  703.36  983.19 1253.79 1830.53 2946.79
River Rch & RM=6945,19,6496.998
  479.42   810.9 1136.17 1451.65 2119.42 3355.79
River Rch & RM=6945,19,5805.733
  485.92  822.14 1152.17 1472.35 2149.63  3398.1
River Rch & RM=6945,19,5090.311
  523.54  887.48 1245.36 1593.16 2326.02 3644.71
River Rch & RM=6945,19,4229.517
  526.36  892.37 1252.33 1602.18 2339.18 3662.94
Boundary for River Rch & Prof#=6945,19,1
Up Type= 0
Dn Type= 2
Boundary for River Rch & Prof#=6945,19,2
Up Type= 0
Dn Type= 2
Boundary for River Rch & Prof#=6945,19,2
Up Type= 0
Dn Type= 2
Boundary for River Rch & Prof#=6945,19,2
Up Type= 0
Dn Type= 2
Boundary for River Rch & Prof#=6945,19,2
Up Type= 0
Dn Type= 2
Boundary for River Rch & Prof#=6945,19,2
Up Type= 0
Dn Type= 2

--- 6945_ras.g01 (geometry) ---

Geom Title=6945
Program Version=4.10

River Reach=6945,19
Reach XY= 30
385633.461321056848520.630875289385751.733890563848607.436430871
385756.074168354848735.474625304385938.365834951848843.981569752
385652.992571026849060.995458692385862.410973817849230.266291991
385738.713057101849860.691639185385838.673520923850363.711663395
385968.855589896850550.741018713 385806.24777934850977.835736394
386073.608890444851525.057958663385856.247779369851857.002403095
386202.674284101852235.000088289386132.301803827852783.000135198
386298.100414962852906.264024109386239.940692723853190.986246347
386618.412914962853134.562635228  386551.5726372853403.659857437
386710.426803827853469.632079676386706.954581648 853902.79180187
386550.921595514854409.085204661386614.940692723854616.333468586
386851.051803827854434.041801885387048.968470752854515.639024153
387003.829581618854644.111246333387120.149026066854727.444579646
387139.246248275854875.014024124387040.287914991854930.569579661
386944.801803857854859.389024153386967.203879088854990.161884055

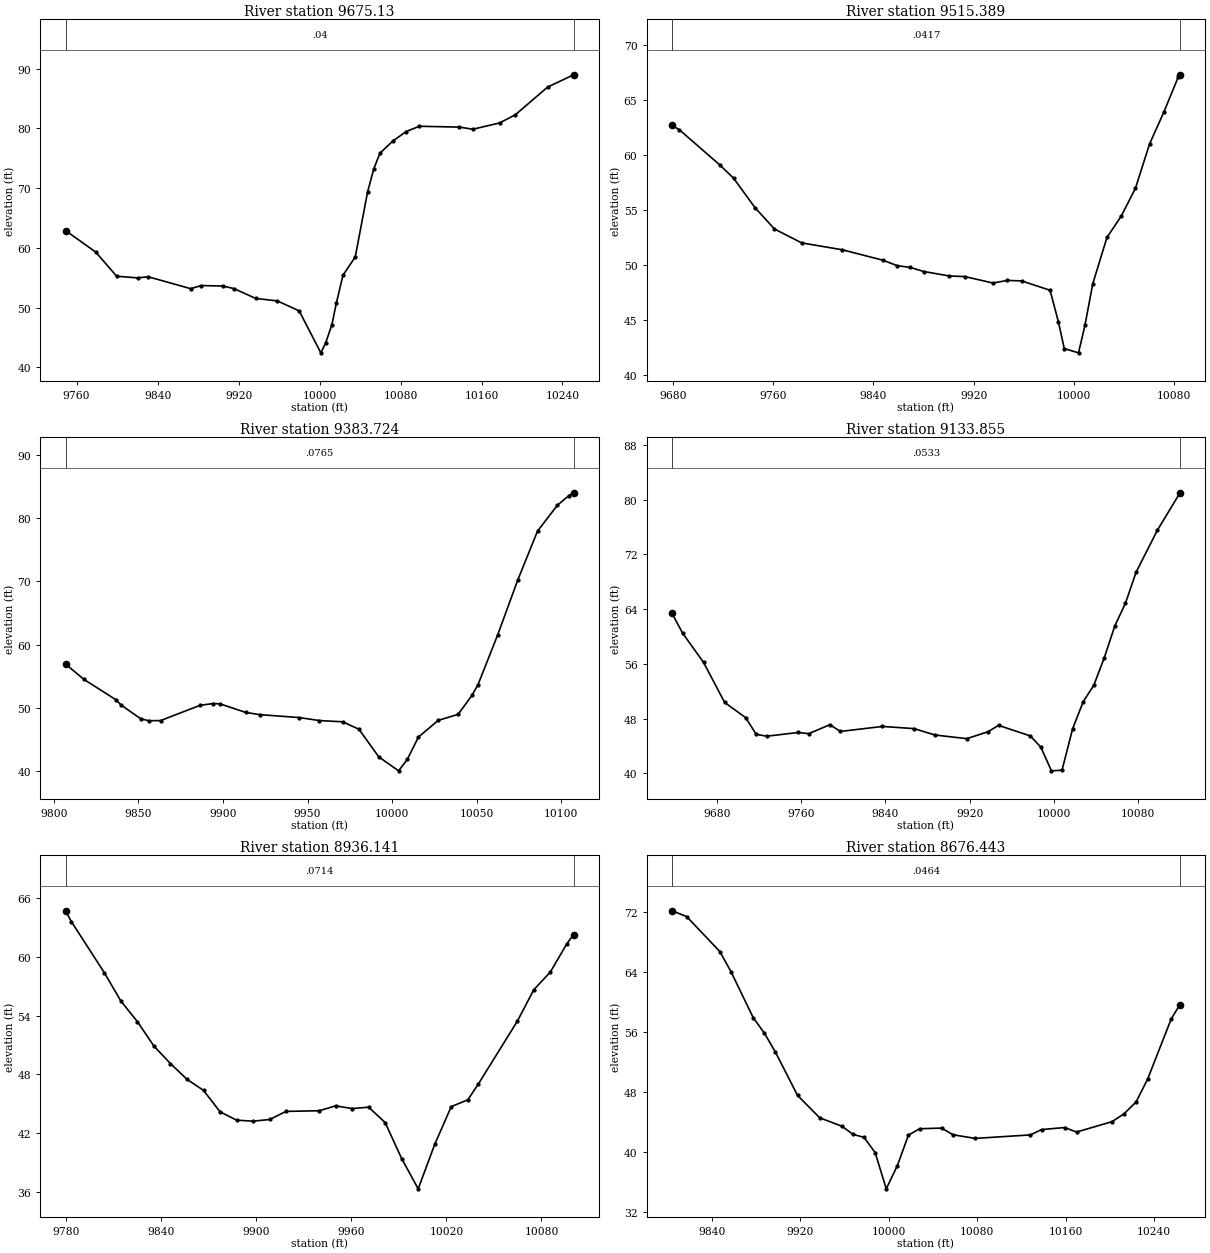
Type RM Length L Ch R = 1 , 9675.13,159.740300,159.740300,159.740300
XS GIS Cut Line= 6
385395.981220374848600.589338993385465.953727862848583.017684526
385518.175127754848566.529565018385655.611173375848511.916825008
385690.377845096848487.867614288385831.655471141848368.797831826
#Sta/Elev= 30
9749.034 62.89989778.95459.278059799.57555.253079820.19654.976739830.66655.16605
9872.61253.173879883.26553.692689904.726  53.6089915.45653.181219936.91651.53755
9958.37651.119839979.83749.4596510001.2842.4340810005.9844.0708510012.1647.12205
10016.5650.7386310023.1955.4356110035.2858.4829910047.4469.34596 10053.673.22644
 10059.675.8266910072.2477.8487510085.4479.4513410098.6480.3448410138.2480.20335
10151.4479.8463110177.8480.8979610193.4782.2706410225.21 86.888910250.9288.95744
#Mann= 3 , 0 , 0
9749.034    0.04       09749.034    0.04       010250.92    0.04       0
#XS Ineff= 2 , 0
       0                               0
Bank Sta=9749.034,10250.92
Exp/Cntr=0.3,0.1

Type RM Length L Ch R = 1 ,9515.389,131.665500,131.665500,131.665500
XS GIS Cut Line= 3
385459.619660228 848740.62933442385676.633549094848649.483501092
385826.373132452848569.188362181
#Sta/Elev= 30
9679.40662.650639685.24262.27161 9717.7859.043239728.62657.848179745.59255.19271
9761.16553.244559782.85751.983779815.39651.354319847.93550.400329858.78149.92395
9869.62749.747119880.47349.379299900.53848.979739913.01248.920269935.62448.33407
9946.97148.573079958.31848.528049981.01247.678429987.75344.772849992.35942.37862
10003.7141.9914110008.9144.5190310015.0548.24977 10026.452.4764110037.75 54.4086
10049.0956.9299410060.4460.9849610071.7963.8637810083.1467.0152810084.6967.25974
#Mann= 3 , 0 , 0
9679.406  0.0417       09679.406  0.0417       010084.69  0.0417       0
#XS Ineff= 2 , 0
       09872.562                       0
Bank Sta=9679.406,10084.69
Exp/Cntr=0.3,0.1

Type RM Length L Ch R = 1 ,9383.724,249.869400,249.869400,249.869400
XS GIS Cut Line= 2
385587.093618557848830.704565898385843.170007452 848673.58651033
#Sta/Elev= 30
 9806.8456.905219817.74854.480129836.869 51.2185 9839.5850.448959851.31248.24331
9855.99147.936249863.045 47.95549886.50950.380659894.23450.658079898.24150.60252
9913.35649.251569921.70648.89591 9945.1748.433949956.90347.963219970.72147.76431
9980.36746.585959992.099 42.211710003.8340.0008410008.9641.8060810015.5645.35729
 10027.347.9986810039.0348.9456310047.2151.9566310050.7653.6341810062.4961.57926
10074.23 70.177310085.9677.9475810097.6982.0417810104.5783.5924610107.2784.02378
#Mann= 3 , 0 , 0
 9806.84  0.0765       0 9806.84  0.0765       010107.27  0.0765       0
#XS Ineff= 2 , 0
       09935.318                       0
Bank Sta=9806.84,10107.27
Exp/Cntr=0.3,0.1

Type RM Length L Ch R = 1 ,9133.855,197.713800,197.713800,197.713800
XS GIS Cut Line= 3
385574.940840766848859.350399226385830.843618557848862.533269584
 386056.53806299848838.661741823
#Sta/Elev= 30
9637.08463.398599647.14460.500869667.146 56.20459687.14850.364619707.14948.14009
 9717.15 45.70679727.15145.430749757.15345.976739767.15445.802349787.15547.11655
9797.156 46.12819837.15946.857849867.16146.544489887.16345.604779917.29845.07533
 9937.4146.079879947.46647.019039977.63345.473029987.68943.833439997.74440.37195
 10007.840.4626310017.86 46.500210027.9150.4696110037.9752.8518810048.02 56.9147
10058.0861.5836210068.1364.8723610078.1969.38917 10098.375.4894210119.9681.00002
#Mann= 3 , 0 , 0
9637.084  0.0533       09637.084  0.0533       010119.96  0.0533       0
#XS Ineff= 2 , 0
       0 9781.49                       0
Bank Sta=9637.084,10119.96
Exp/Cntr=0.3,0.1

Type RM Length L Ch R = 1 ,8936.141,259.698000,259.698000,259.698000
XS GIS Cut Line= 2
385571.425215781 848871.09808442385879.064104676848962.070306629
#Sta/Elev= 30
9779.44364.704799783.17163.594629804.02758.368569814.45555.479889824.88353.38076
9835.31150.88962 9845.7449.105369856.16847.500969866.59646.373379877.02444.19188
9887.45243.33761 9897.88  43.2299908.30843.401669918.736 44.22919939.592 44.2948
 9950.02  44.7949960.448 44.51769970.87644.657619981.30443.084959991.73239.40705
10002.1636.3241810012.5940.8630210023.0244.7166810033.4445.4035310040.0546.99833
10064.7353.4293210075.1656.6500110085.5858.4465610096.01  61.33810100.2562.28004
#Mann= 3 , 0 , 0
9779.443  0.0714       09779.443  0.0714       010100.25  0.0714       0
#XS Ineff= 2 , 0
       09875.029                       0
Bank Sta=9779.443,10100.25
Exp/Cntr=0.3,0.1

Type RM Length L Ch R = 1 ,8676.443,256.234200,256.234200,256.234200
XS GIS Cut Line= 3
385461.789799107849090.021695517385802.528521063 849062.97672254
385912.370394585849020.731940809
#Sta/Elev= 30
9803.91672.128129817.16771.361399847.26266.694139857.29364.019839877.35657.90981
9887.38855.861319897.41953.331419917.48247.552259937.54544.566869957.60843.44334
9967.63942.364719977.67141.961399987.70239.923569997.73435.1096410007.7638.20434
 10017.842.2628210027.83 43.109410047.8943.1980210057.9242.3153610077.9941.82603
10128.1442.2884610138.1743.0005810159.0943.27103 10169.842.6696710201.94 44.0562
10212.6645.0870310223.6646.6722710234.0949.7054910255.5157.7511510263.4159.64953
#Mann= 3 , 0 , 0
9803.916  0.0464       09803.916  0.0464       010263.41  0.0464       0
#XS Ineff= 2 , 0
       0                               0
Bank Sta=9803.916,10263.41
Exp/Cntr=0.3,0.1

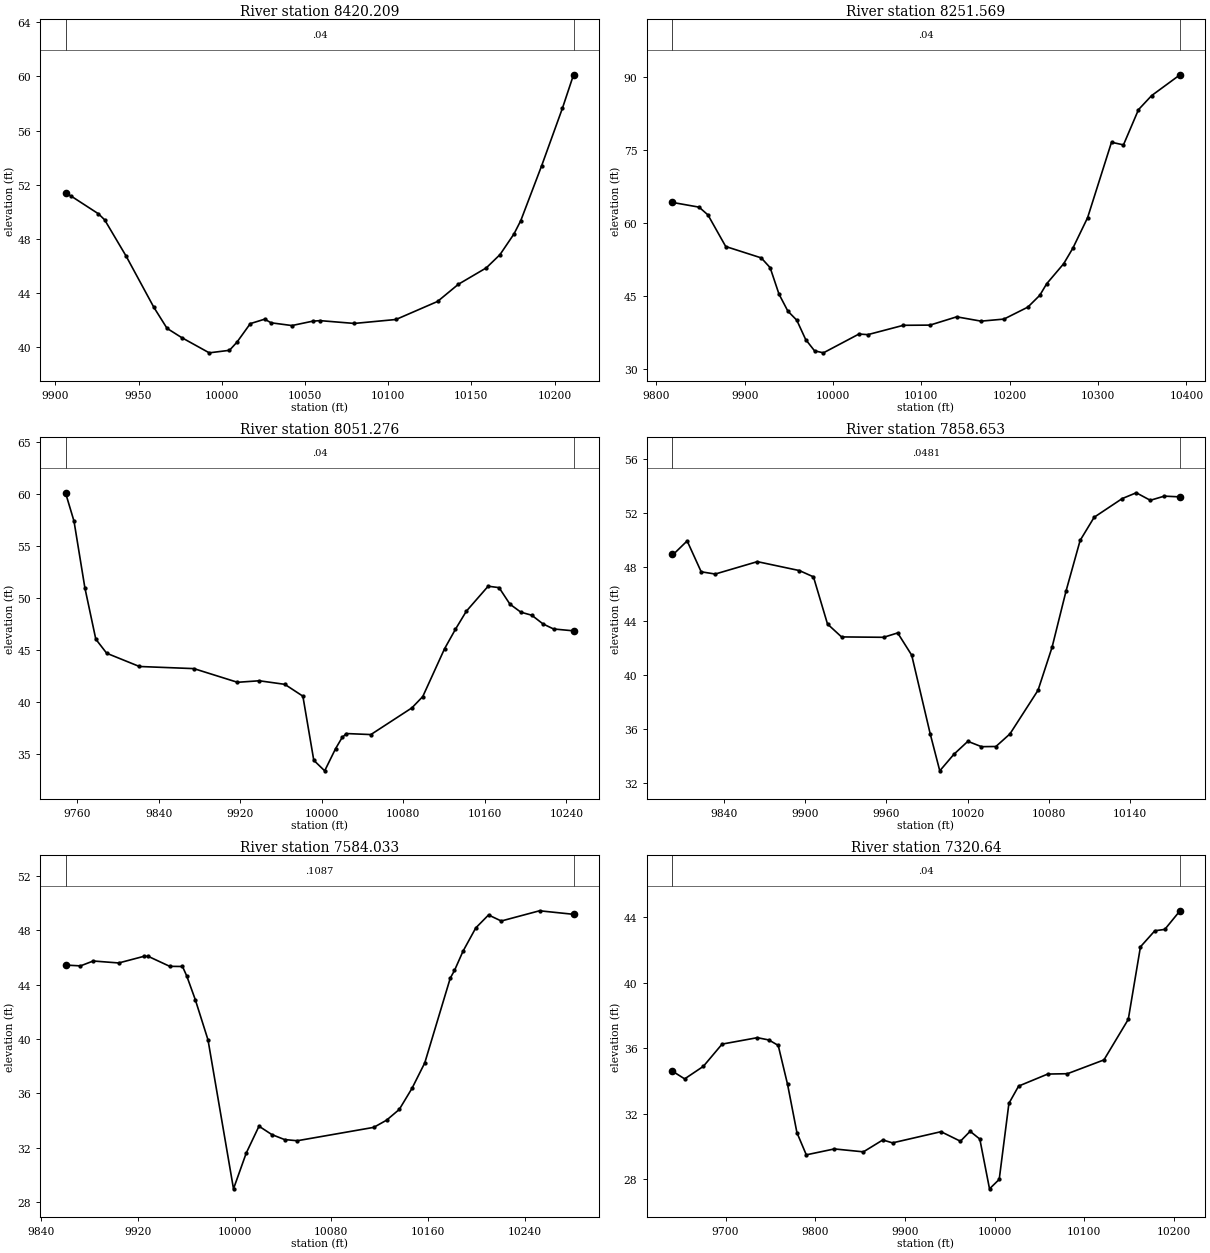
Type RM Length L Ch R = 1 ,8420.209,168.639700,168.639700,168.639700
XS GIS Cut Line= 2
385746.208201885849236.882227927  385990.3488269849053.505491823
#Sta/Elev= 28
9906.08151.345929909.21651.166559925.86649.836779929.58449.394019942.51746.70427
9959.16842.919679967.104 41.35989975.81940.68209 9992.4739.5478810004.6239.73537
10009.1240.3362710017.13  41.70910025.7742.0388910029.6441.7708110042.1441.56735
10054.6541.8911610059.0741.9310410079.6641.7235410104.6842.0155710129.6943.35054
 10142.244.6217410158.9845.8357610167.2146.8147510175.6348.3478710179.7249.33758
10192.2853.4019710204.7357.6470210211.4260.12427
#Mann= 3 , 0 , 0
9906.081    0.04       09906.081    0.04       010211.42    0.04       0
#XS Ineff= 2 , 0
       0                               0
Bank Sta=9906.081,10211.42
Exp/Cntr=0.3,0.1

Type RM Length L Ch R = 1 ,8251.569,200.292900,200.292900,200.292900
XS GIS Cut Line= 3
 385654.49813244 849308.77169552385976.785340427849342.386945261
386162.310632452849173.355028851
#Sta/Elev= 30
9817.709 64.21489848.37663.23052 9858.4361.636099878.53955.159739918.75652.82518
 9928.8150.826139938.86445.389549948.91841.900999958.97340.056759969.02736.09266
9979.08133.776399989.13533.3615510029.3537.2163410039.4137.0924610079.62  39.006
10109.7939.0472610139.9540.7434710167.5639.8589310193.4440.27943 10220.542.73508
10234.0345.16026 10241.847.5211910261.0851.63651 10271.554.8347510288.1461.07393
10315.1976.5335410328.7275.9941510345.7483.2214410360.5986.0967410392.7390.36623
#Mann= 3 , 0 , 0
9817.709    0.04       09817.709    0.04       010392.73    0.04       0
#XS Ineff= 2 , 0
       0                               0
Bank Sta=9817.709,10392.73
Exp/Cntr=0.3,0.1

Type RM Length L Ch R = 1 ,8051.276,192.623500,192.623500,192.623500
XS GIS Cut Line= 2
385597.206465766849428.563362181386063.352299109849605.646695539
#Sta/Elev= 30
9748.49660.099179756.83357.37915 9767.5350.973199778.22846.060619788.92544.70877
9821.01743.439279874.50343.235199917.29241.923419938.68742.069299963.73441.72773
9981.476 40.59279992.17334.4459210002.8733.4314610013.5735.5583910020.0536.63416
10024.2637.0074510048.2136.9101310088.4539.4682310099.1540.5553510120.5445.14225
10131.24 47.011610141.9348.7427510163.3351.1389310174.03 51.001510184.7249.41645
10195.4248.6486810206.1248.3555610217.1647.5218510227.5147.0378710247.1446.85835
#Mann= 3 , 0 , 0
9748.496    0.04       09748.496    0.04       010247.14    0.04       0
#XS Ineff= 2 , 0
       0                               0
Bank Sta=9748.496,10247.14
Exp/Cntr=0.3,0.1

Type RM Length L Ch R = 1 ,7858.653,274.619000,274.619000,274.619000
XS GIS Cut Line= 2
385584.185632437849644.709195524385946.164799094849743.667528853
#Sta/Elev= 30
9801.57449.020299802.67748.975389812.78549.962169823.152 47.67519833.51947.50912
 9864.6248.427099895.72147.765259906.088    47.39916.45543.808029926.82142.85233
9957.922 42.82389968.28943.147499978.65641.499779992.28335.68946 9999.3932.93355
10009.7634.1530510020.1235.11943 10030.234.7232810040.8634.7361310051.22 35.6688
10071.9638.9008710082.3342.0854910092.6946.2648310103.0649.9985410113.4351.71524
10134.1653.0991410144.5353.5274910154.8952.9710710165.2653.2791910176.84 53.2241
#Mann= 3 , 0 , 0
9801.574  0.0481       09801.574  0.0481       010176.84  0.0481       0
#XS Ineff= 2 , 0
       0                               0
Bank Sta=9801.574,10176.84
Exp/Cntr=0.3,0.1

Type RM Length L Ch R = 1 ,7584.033,263.393300,263.393300,263.393300
XS GIS Cut Line= 2
385623.248132437850006.688362211386021.685632452849873.875862211
#Sta/Elev= 30
9860.23445.451189872.62145.390959883.16245.749999904.24445.605879925.32646.10069
9928.81846.084289946.40845.357029956.94945.346189960.44144.65182 9967.4942.91273
9978.03139.945079999.11228.9767210009.6531.6125310020.1933.5887310030.74 32.9747
10041.28  32.60510051.8232.5175610115.0633.50304 10125.634.0285610136.1434.82066
10146.6936.3787810157.2338.2498810178.3144.49097 10181.845.0530910188.8546.47198
10199.3948.1857610209.9349.1386210220.4748.6949910252.0949.4475310280.2249.18701
#Mann= 3 , 0 , 0
9860.234  0.1087       09860.234  0.1087       010280.22  0.1087       0
#XS Ineff= 2 , 0
       0                               0
Bank Sta=9860.234,10280.22
Exp/Cntr=0.3,0.1

Type RM Length L Ch R = 1 , 7320.64,378.279100,378.279100,378.279100
XS GIS Cut Line= 4
385491.433896334850227.984658494385666.167403959850279.690934735
385903.760285217850181.977714067385997.510285208850096.040214058
#Sta/Elev= 30
9640.32534.608879654.47334.12015 9675.33 34.88769696.18836.246269735.53336.63959
9748.33136.498339758.759 36.16669769.18833.778829779.61730.832499790.04529.47625
9821.33129.837559853.72529.65933 9875.3530.386769886.16330.207579940.22630.89166
9961.85130.308649972.66430.915659983.476 30.44049994.28927.39766 10005.1 27.9753
10015.9132.6236210026.7333.6798310059.1734.4151910081.1334.4359510121.8335.28002
10148.9737.7607510162.5342.1935410178.5743.1761310189.6643.2582810206.63 44.3974
#Mann= 3 , 0 , 0
9640.325    0.04       09640.325    0.04       010206.63    0.04       0
#XS Ineff= 2 , 0
       09861.732        10049.81       0
Bank Sta=9640.325,10206.63
Exp/Cntr=0.3,0.1

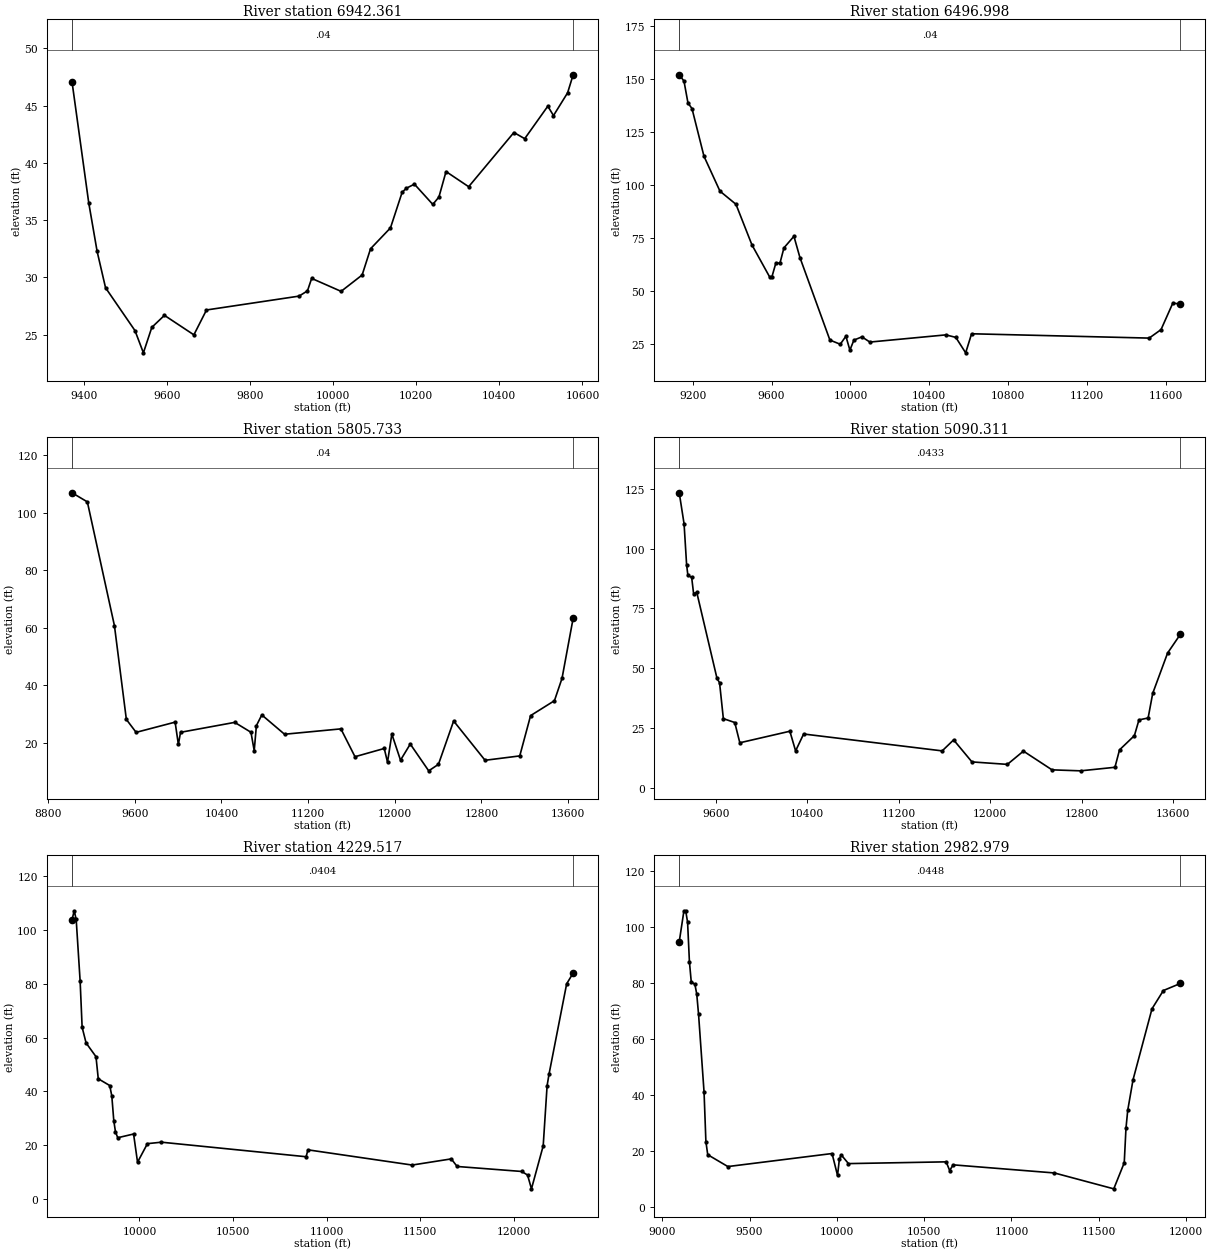
Type RM Length L Ch R = 1 ,6942.361,445.363600,445.363600,445.363600
XS GIS Cut Line= 3
 385345.33865595 850623.56917504386119.488425619850502.315574039
386429.786779257850215.934767455
#Sta/Elev= 30
9371.86247.071539412.00736.52283 9432.2532.269129452.49429.098679523.34825.35626
9543.59223.417369563.83525.641039594.20126.690579665.05524.98861 9695.4227.15979
9918.10328.369579938.34628.825949948.46829.9163610019.3228.7851910069.9330.21191
10090.1832.50513 10138.134.3247210166.2437.4411610176.5637.7918210195.7338.14465
10239.96 36.3749 10254.737.0214510271.8139.2446710326.2537.9214410435.1142.65435
10461.1342.1153310516.7644.9531910530.3744.1307410564.3446.11885 10577.747.69386
#Mann= 3 , 0 , 0
9371.862    0.04       09371.862    0.04       0 10577.7    0.04       0
#XS Ineff= 2 , 0
       09732.027        10042.07       0
Bank Sta=9371.862,10577.7
Exp/Cntr=0.3,0.1

Type RM Length L Ch R = 1 ,6496.998,691.264100,691.264100,691.264100
XS GIS Cut Line= 4
384971.253264923851080.106360276 386342.78104269850850.071638101
386464.308820434850845.731360237387492.988478496850799.474837674
#Sta/Elev= 30
9131.766  152.049155.844149.06289176.124138.69729196.403136.13429257.241113.6215
9338.35997.162899419.47690.981229500.59371.82102 9591.85 56.4568 9601.9956.81272
9622.26963.374719642.54963.166389662.82870.419079713.52775.884819743.946 65.8803
9896.04126.952159948.55724.977999977.15828.759589997.43822.2069610017.72 26.9288
10058.2828.4595410098.83 26.012210484.14 29.398510534.6828.2252110584.7120.93032
10614.7329.9223811515.6327.8807411575.6931.8801711635.7544.4235211673.7843.87056
#Mann= 3 , 0 , 0
9131.766    0.04       09131.766    0.04       011673.78    0.04       0
#XS Ineff= 2 , 0
       09870.256        10155.89       0
Bank Sta=9131.766,11673.78
Exp/Cntr=0.3,0.1

Type RM Length L Ch R = 1 ,5805.733,715.422800,715.422800,715.422800
XS GIS Cut Line= 4
385093.649098228851574.029971458386645.732431545851521.946638098
387225.000000013851508.791544443389717.631923807851400.967435283
#Sta/Elev= 30
9020.008106.97199161.439103.8007 9411.5860.692259521.64228.051689611.69223.55587
9971.89527.1146210001.9119.3504210021.9223.56994 10522.227.0315910672.2623.58577
10702.2717.1732510722.2725.8797610772.2829.6250510982.3422.8983511502.7124.76915
11632.8315.0738811903.08 17.947311933.1113.1560511973.1522.9438712053.2213.87353
12143.3119.4823112313.4710.1573212403.5512.4260912543.68 27.510812833.9513.83172
13154.2515.3554713254.3529.3824113474.5534.5789613544.6242.3670613647.3563.29765
#Mann= 3 , 0 , 0
9020.008    0.04       09020.008    0.04       013647.35    0.04       0
#XS Ineff= 2 , 0
       09937.915        10221.16       0
Bank Sta=9020.008,13647.35
Exp/Cntr=0.3,0.1

Type RM Length L Ch R = 1 ,5090.311,860.794000,860.794000,860.794000
XS GIS Cut Line= 5
385416.855116739852359.041545483386018.571877162852072.200432574
386099.602515122 852047.66738267386966.334283393852107.305434352
389726.750950073852046.541545459
#Sta/Elev= 30
 9281.65123.42769323.908110.42549346.06493.281639357.14288.893259390.37787.96433
9407.23781.176519434.68981.766839611.93945.681659634.09543.913259667.32928.87195
9767.03327.242929811.34518.7619110248.8123.5933710298.9315.3600710369.09 22.4366
11580.5115.3668711680.5419.9741611840.5810.7534612150.659.71750912290.6915.27001
12540.757.42811312790.817.01331713090.888.50017813130.8915.7930813260.9221.75108
13300.9328.3430513380.9529.1404713420.9639.4382613550.9956.3117813662.7764.16876
#Mann= 3 , 0 , 0
 9281.65  0.0433       0 9281.65  0.0433       013662.77  0.0433       0
#XS Ineff= 2 , 0
       09936.887        10444.01       0
Bank Sta=9281.65,13662.77
Exp/Cntr=0.3,0.1

Type RM Length L Ch R = 1 ,4229.517,1246.537100,1246.537100,1246.537100
XS GIS Cut Line= 4
 385804.00789462852920.673489928386317.896783382852743.590156585
387439.424561173852778.312378809388408.174561188853073.451267704
#Sta/Elev= 30
  9639.5103.89059651.126107.21059661.704103.98839682.85880.964899693.43563.88149
9714.58958.048729767.47452.945569779.69144.71773 9841.0842.198339852.09138.30917
9862.66829.119639871.77424.929999883.82222.786579968.43924.169059989.59313.68112
10042.4820.5845710117.3321.1269210890.4915.7158610900.4918.2825411457.2912.62416
11666.3714.9170611697.7312.09419 12042.7 10.241112074.068.91351312094.973.775352
12157.6919.74953 12178.642.1688512189.0646.5132612283.1480.0458112317.8284.04562
#Mann= 3 , 0 , 0
  9639.5  0.0404       0  9639.5  0.0404       012317.82  0.0404       0
#XS Ineff= 2 , 0
       09897.827        10681.15       0
Bank Sta=9639.5,12317.82
Exp/Cntr=0.3,0.1

Type RM Length L Ch R = 1 ,2982.979,910.806300,910.806300,910.806300
XS GIS Cut Line= 5
385689.424561173853667.201267689386314.424561188853469.284601033
386835.257894516853313.034601018388231.091227919853326.923489943
388484.563450173853219.284601018
#Sta/Elev= 30
9097.09794.693219123.924105.76889134.413105.63619144.903101.67289155.39287.58713
9165.88180.39377 9186.8679.50679 9197.3576.039049207.83968.741399239.30740.95822
9249.79723.361569260.28618.68659 9375.67  14.4529972.53219.1032110003.8511.27514
10014.2917.0351110024.7318.6402310066.4915.5089510626.2116.1383310646.2113.02871
10666.2115.0661911246.2412.1670711586.266.49893711646.2615.8032611656.2628.18644
11666.2634.53886 11696.645.4337911805.24 70.781311870.4377.2973211967.7379.82169
#Mann= 3 , 0 , 0
9097.097  0.0448       09097.097  0.0448       011967.73  0.0448       0
#XS Ineff= 2 , 0
       09782.373        10492.75       0
Bank Sta=9097.097,11967.73
Exp/Cntr=0.3,0.1

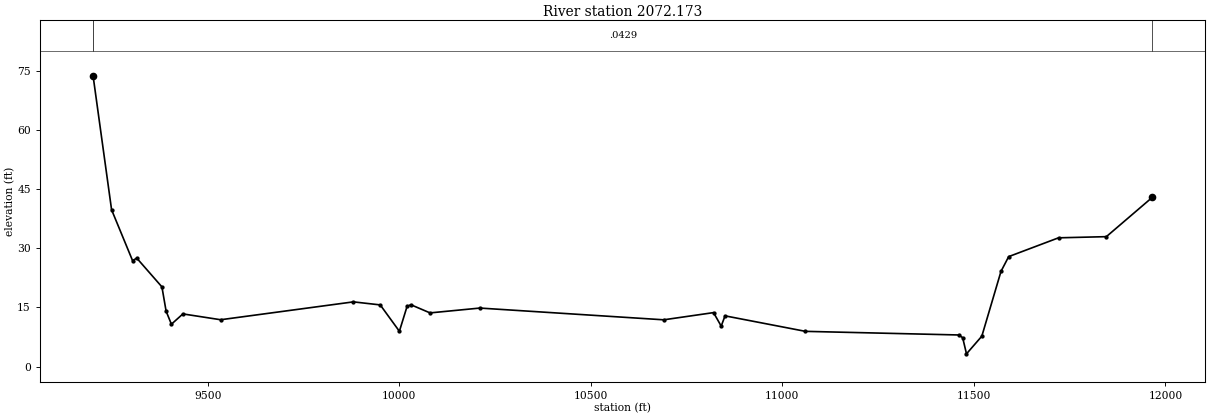
Type RM Length L Ch R = 1 ,2072.173,0.000000,0.000000,0.000000
XS GIS Cut Line= 5
385850.882894576853861.645712122386434.216227829854122.062378809
387767.549561173854142.895712152388361.299561173 854116.85404548
388547.963568747854048.283593714
#Sta/Elev= 30
9200.733 73.79979249.04739.788259303.80326.880179314.75427.517259380.46220.21299
9391.413 14.03979405.20710.737189435.21813.351959533.77911.872129880.34416.40792
9950.35315.6378110000.368.94468910020.36 15.235410030.3615.6816110080.3713.60891
10210.3814.8357910690.4411.8541110820.4613.6804110840.46 10.252510850.4612.85949
11060.49 8.9230711460.788.00509411470.79 7.31521 11480.83.21634811520.847.697479
11570.8824.15385 11590.927.8942811721.0332.6665211845.8932.9609711966.2342.97142
#Mann= 3 , 0 , 0
9200.733  0.0429       09200.733  0.0429       011966.23  0.0429       0
#XS Ineff= 2 , 0
       09758.041        10450.56       0
Bank Sta=9200.733,11966.23
Exp/Cntr=0.3,0.1